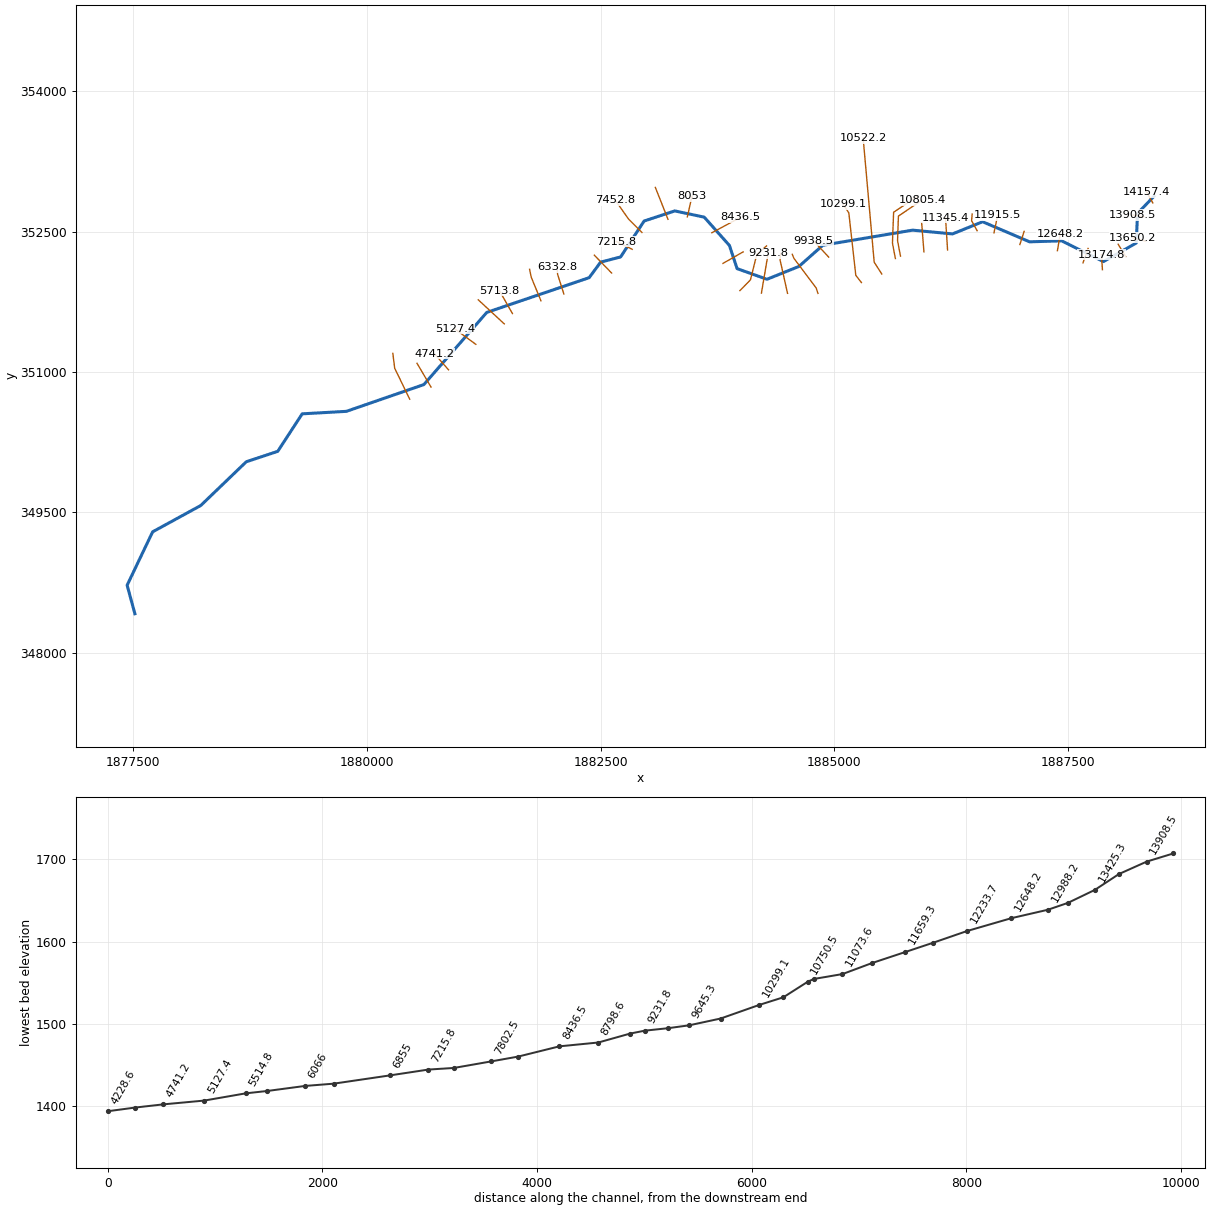
--- SQUIRESCRK.prj (project) ---

Proj Title=SQUIRESCRK
Current Plan=p01
Geom File=g01
Flow File=f01
Plan File=p01
DSS Export Rating Curves=0
DSS Export Rating Curve Sorted=0
DSS Export Volume Flow Curves=0
DXF OffsetX=0
DXF OffsetY=0
DXF ScaleX=0
DXF ScaleY=0

--- SQUIRESCRK.p01 (plan) ---

Plan Title=Floodplain
Program Version=4.00
Geom File=g01
Flow File=f01
K Sum by GR=0
Std Step Tol=0.01
Critical Tol=0.01
Num of Std Step Trials=20
Max Error Tol=0.3
Flow Tol Ratio=0.001
Split Flow NTrial=30
Split Flow Tol=0.02
Split Flow Ratio=0.02
Log Output Level=0
Friction Slope Method=1
Unsteady Friction Slope Method=2
Unsteady Bridges Friction Slope Method=1
Global Log Level=0
CheckData=False
Run HTab=0
Run UNet=0
Run PostProcess=0
UNET Theta=0
UNET Theta Warmup=0
UNET ZTol=0
UNET ZSATol=0
UNET MxIter=0
UNET MaxInSteps=0
UNET DtIC=0
UNET DtMin=0
UNET MaxCRTS=0
UNET WFStab=0
UNET SFStab=0
UNET WFX=0
UNET SFX=0
UNET DSS MLevel=0
UNET DZMax Abort=0
UNET Convert EG Bridges=0
UNET Use Existing IB Tables=0
UNET Froude Limit=0
UNET Froude Power=0
Write IC File=0
Echo Input=False
Echo Output=False
Write Detailed=0

--- SQUIRESCRK.f01 (steady flow) ---

Flow Title=NFF Regression Equation
Program Version=4.10
Number of Profiles= 1
Profile Names=P100yr
River Rch & RM=SQUIRESCRK,Main            ,14157.4
532.7795
River Rch & RM=SQUIRESCRK,Main            ,10522.2
573.4355
River Rch & RM=SQUIRESCRK,Main            ,9938.5
835.1385
River Rch & RM=SQUIRESCRK,Main            ,6332.8
 910.003
River Rch & RM=SQUIRESCRK,Main            ,4228.6
950.5075
Boundary for River Rch & Prof#=SQUIRESCRK,Main            , 1
Up Type= 0
Dn Type= 1
Dn Known WS=1346.46
DSS Import GetInterval= 0
DSS Import GetPeak= 0
DSS Import FillOption= 0

--- SQUIRESCRK.g01 (geometry) ---

Geom Title=USGS 10m DEM
Program Version=4.10

River Reach=SQUIRESCRK      ,Main
Reach XY= 30
     1888417.693      352879.755      1888240.61      352695.728
     1888227.492       352379.28      1887875.93      352180.531
     1887429.846      352402.325      1887086.78      352391.919
     1886584.514       352606.37     1886262.574      352476.326
     1885835.965      352516.502     1884876.561      352355.168
     1884620.697      352128.577     1884279.463      351991.414
     1883959.975      352105.159     1883878.012       352352.72
     1883608.705      352655.481     1883293.898      352722.214
     1882965.773      352614.142     1882714.471      352230.027
     1882500.982      352174.703     1882378.534      352008.673
     1881283.482      351637.058     1880611.607      350865.965
     1879783.221      350579.506     1879310.565      350552.944
     1879048.846      350151.902     1878712.909      350040.704
      1878225.93      349572.735     1877711.607      349291.485
      1877438.95      348720.652      1877521.84      348415.688

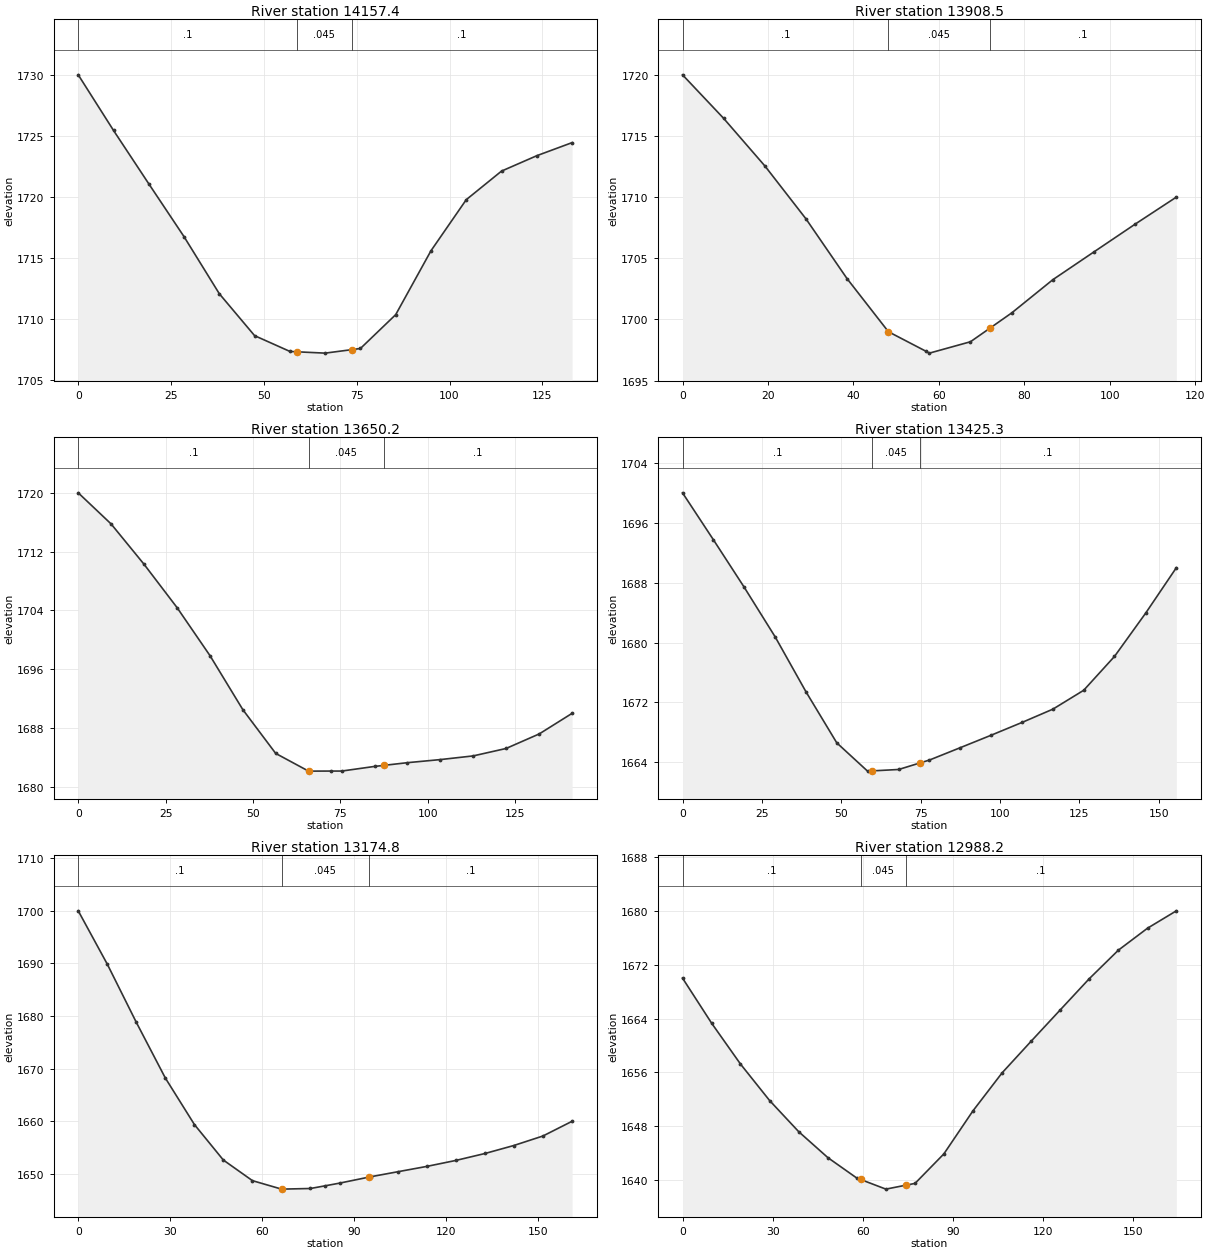
Type RM Length L Ch R = 1 ,14157.4 ,228.1,249,269.6
XS GIS Cut Line= 2
     1888404.181      352807.734     1888339.394      352923.853
#Sta/Elev= 17
       0 1729.99     9.5 1725.44      19 1721.07    28.5 1716.74      38 1712.07
    47.5 1708.64      57 1707.35    58.8 1707.32    66.5 1707.21    73.8  1707.5
      76 1707.59    85.5 1710.36      95 1715.59   104.5 1719.77     114 1722.11
   123.5 1723.37     133 1724.44
#Mann= 3 , 0 , 0
       0      .1       0    58.8    .045       0    73.8      .1       0
Bank Sta=58.8,73.8
XS Rating Curve= 0 ,0
Exp/Cntr=0.3,0.1

Type RM Length L Ch R = 1 ,13908.5 ,260.7,258.3,255.9
XS GIS Cut Line= 2
     1888305.729      352660.128     1888191.556      352678.354
#Sta/Elev= 15
       0    1720     9.6 1716.45    19.3 1712.54    28.9 1708.22    38.5 1703.34
    48.2 1698.99      57 1697.39    57.8 1697.24    67.4 1698.17      72 1699.29
    77.1 1700.54    86.7 1703.25    96.4 1705.54     106  1707.8   115.6    1710
#Mann= 3 , 0 , 0
       0      .1       0    48.2    .045       0      72      .1       0
Bank Sta=48.2,72
XS Rating Curve= 0 ,0
Exp/Cntr=0.3,0.1

Type RM Length L Ch R = 1 ,13650.2 ,242.1,224.9,207.7
XS GIS Cut Line= 2
     1888328.027      352398.966     1888191.556       352435.51
#Sta/Elev= 18
       0    1720     9.4 1715.77    18.8  1710.3    28.3 1704.37    37.7 1697.85
    47.1  1690.5    56.5 1684.55    65.9 1682.14    72.4 1682.15    75.4 1682.15
    84.8 1682.78    87.4 1682.92    94.2 1683.29   103.6 1683.71     113 1684.21
   122.4 1685.22   131.9  1687.2   141.3    1690
#Mann= 3 , 0 , 0
       0      .1       0    65.9    .045       0    87.4      .1       0
Bank Sta=65.9,87.4
XS Rating Curve= 0 ,0
Exp/Cntr=0.3,0.1

Type RM Length L Ch R = 1 ,13425.3 ,261.4,250.4,239.4
XS GIS Cut Line= 2
      1888114.23      352232.968     1888034.077      352366.319
#Sta/Elev= 19
       0    1700     9.7 1693.75    19.4 1687.41    29.2 1680.75    38.9 1673.42
    48.6  1666.6    58.3 1662.82    59.7 1662.85    68.1 1663.04    74.7  1663.9
    77.8  1664.3    87.5 1665.95    97.2 1667.61     107 1669.33   116.7  1671.1
   126.4 1673.62   136.1 1678.14   145.9 1683.91   155.6    1690
#Mann= 3 , 0 , 0
       0      .1       0    59.7    .045       0    74.7      .1       0
Bank Sta=59.7,74.7
XS Rating Curve= 0 ,0
Exp/Cntr=0.3,0.1

Type RM Length L Ch R = 1 ,13174.8 ,195.8,186.7,177.5
XS GIS Cut Line= 2
     1887865.631      352094.049     1887854.925      352254.643
#Sta/Elev= 20
       0 1700.02     9.5 1689.84    18.9 1678.84    28.4  1668.2    37.9 1659.33
    47.3  1652.6    56.8 1648.67    66.3 1647.06    75.7 1647.18    80.3 1647.67
    85.2  1648.2    94.7 1649.34    95.3 1649.41   104.1 1650.36   113.6 1651.38
   123.1 1652.52   132.6 1653.84     142 1655.36   151.5 1657.17     161 1659.97
#Mann= 3 , 0 , 0
       0      .1       0    66.3    .045       0    94.7      .1       0
Bank Sta=66.3,94.7
XS Rating Curve= 0 ,0
Exp/Cntr=0.3,0.1

Type RM Length L Ch R = 1 ,12988.2 ,336,339.9,343.7
XS GIS Cut Line= 2
      1887657.71      352166.427     1887712.246       352321.55
#Sta/Elev= 20
       0 1670.01     9.7 1663.31    19.3 1657.25      29 1651.83    38.7  1647.2
    48.4 1643.35      58 1640.33    59.3 1640.11    67.7 1638.68    74.3 1639.26
    77.4 1639.53      87 1643.91    96.7 1650.31   106.4 1655.95   116.1 1660.66
   125.7 1665.27   135.4 1669.92   145.1 1674.16   154.8 1677.42   164.4    1680
#Mann= 3 , 0 , 0
       0      .1       0    59.3    .045       0    74.3      .1       0
Bank Sta=59.3,74.3
XS Rating Curve= 0 ,0
Exp/Cntr=0.3,0.1

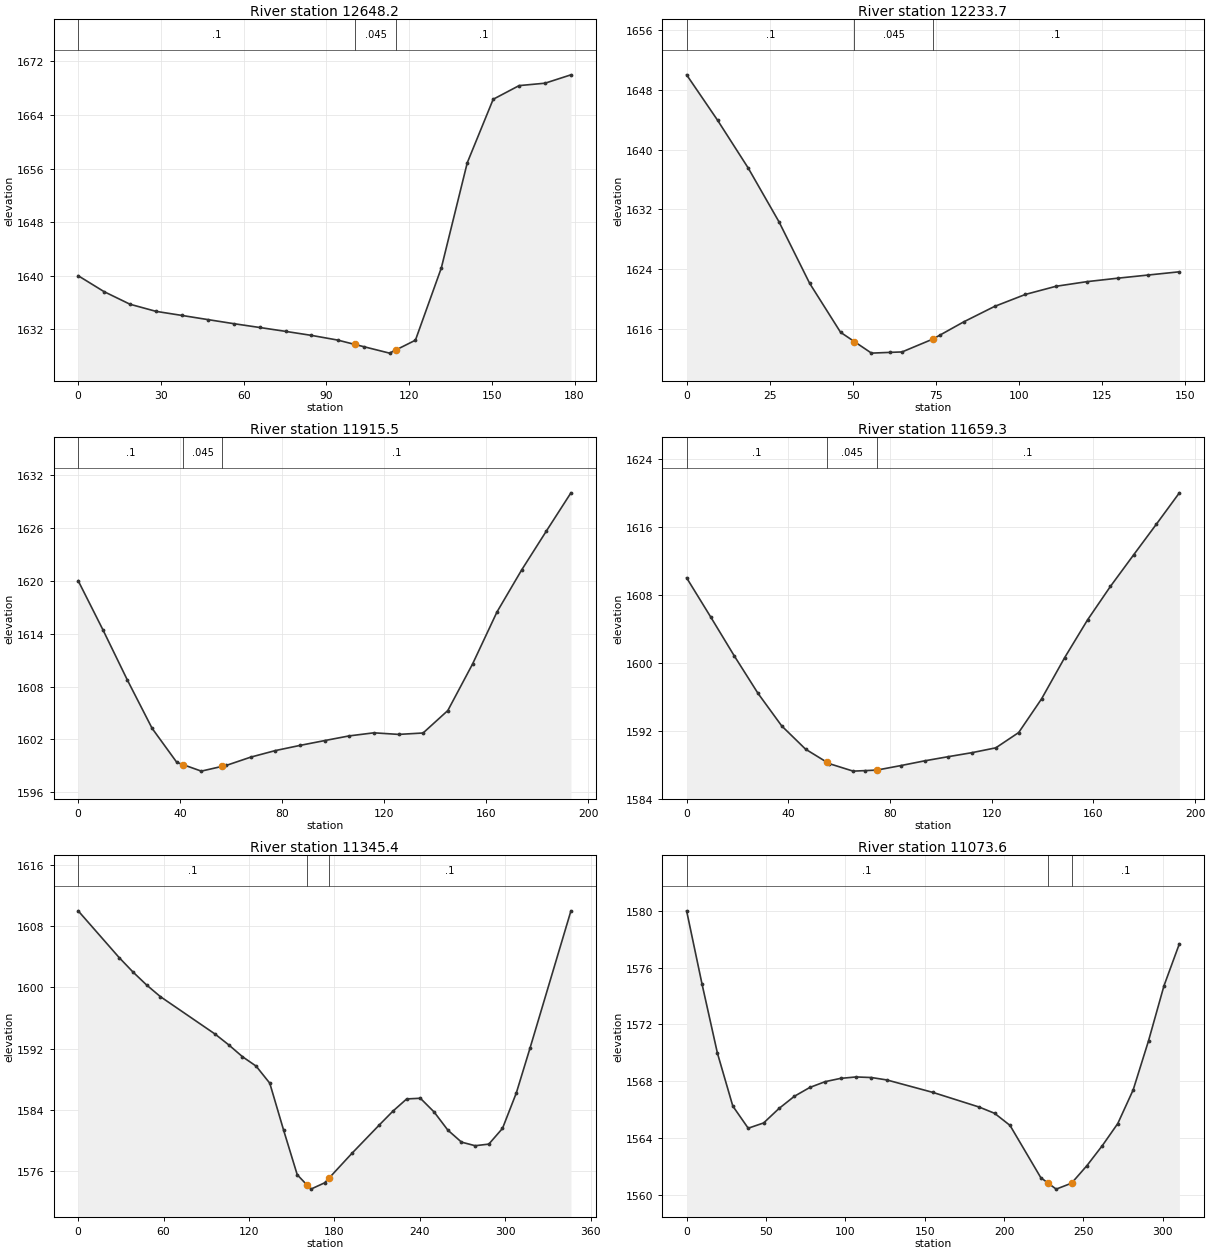
Type RM Length L Ch R = 1 ,12648.2 ,417.8,414.5,411.3
XS GIS Cut Line= 2
     1887384.479      352296.729     1887414.006      352472.979
#Sta/Elev= 22
       0    1640     9.4 1637.62    18.8 1635.74    28.2 1634.68    37.6 1634.07
      47 1633.45    56.4 1632.84    65.8 1632.27    75.2 1631.69    84.6 1631.09
    94.1 1630.39   100.3 1629.74   103.5 1629.41   112.9 1628.44   115.3 1628.93
   122.3 1630.37   131.7 1641.17   141.1 1656.87   150.5 1666.35   159.9 1668.39
   169.3 1668.75   178.7    1670
#Mann= 3 , 0 , 0
       0      .1       0   100.3    .045       0   115.3      .1       0
Bank Sta=100.3,115.3
XS Rating Curve= 0 ,0
Exp/Cntr=0.3,0.1

Type RM Length L Ch R = 1 ,12233.7 ,315.7,318.3,320.4
XS GIS Cut Line= 2
      1886982.82      352362.799     1887028.631      352503.714
#Sta/Elev= 20
       0 1650.01     9.3 1643.94    18.5 1637.55    27.8 1630.32      37  1622.1
    46.3 1615.54   50.481614.286    55.6 1612.75    61.1 1612.85    64.8 1612.91
    74.1 1614.64    76.1 1615.14    83.4 1616.95    92.6    1619   101.9 1620.61
   111.1  1621.7   120.4 1622.32   129.6 1622.78   138.9 1623.21   148.2 1623.64
#Mann= 3 , 0 , 0
       0      .1       0   50.48    .045       0    74.1      .1       0
Bank Sta=50.48,74.1
XS Rating Curve= 0 ,0
Exp/Cntr=0.3,0.1

Type RM Length L Ch R = 1 ,11915.5 ,240.7,256.2,271.6
XS GIS Cut Line= 2
      1886706.19      352488.034     1886746.061      352677.215
#Sta/Elev= 23
       0 1620.02     9.7 1614.45    19.3 1608.74      29 1603.26    38.7 1599.39
    41.3 1599.12    48.3  1598.4    56.3 1598.93      58 1599.04    67.7 1599.99
    77.3 1600.73      87 1601.32    96.7 1601.87   106.3  1602.4     116 1602.75
   125.7 1602.57   135.3 1602.73     145 1605.28   154.7 1610.56   164.3 1616.48
     174 1621.26   183.7 1625.68   193.3    1630
#Mann= 3 , 0 , 0
       0      .1       0    41.3    .045       0    56.3      .1       0
Bank Sta=41.3,56.3
XS Rating Curve= 0 ,0
Exp/Cntr=0.3,0.1

Type RM Length L Ch R = 1 ,11659.3 ,323.9,313.9,303.9
XS GIS Cut Line= 3
     1886525.856      352510.889     1886466.938      352617.272
     1886472.646       352689.23
#Sta/Elev= 24
       0    1610     9.4 1605.43    18.7 1600.84    28.1  1596.4    37.4 1592.58
    46.8 1589.84    55.2  1588.3    56.1 1588.14    65.5 1587.26    70.2 1587.32
    74.8 1587.38    84.2 1587.91    93.6 1588.47   102.9 1588.96   112.2 1589.43
   121.6    1590   130.6  1591.8   139.6 1595.76   148.7 1600.62   157.7 1605.06
   166.7    1609   175.8  1612.7   184.8 1616.33   193.8    1620
#Mann= 3 , 0 , 0
       0      .1       0    55.2    .045       0    74.8      .1       0
Bank Sta=55.2,74.8
XS Rating Curve= 0 ,0
Exp/Cntr=0.3,0.1

Type RM Length L Ch R = 1 ,11345.4 ,271.3,271.8,272.1
XS GIS Cut Line= 2
     1886209.943      352305.156     1886188.051      352650.694
#Sta/Elev= 30
       0    1610    28.8 1603.89    38.5 1602.01    48.1 1600.31    57.7  1598.8
    96.2  1593.9   105.8 1592.49   115.4 1590.95     125 1589.72   134.6 1587.49
   144.3 1581.37   153.9 1575.53     161 1574.14   163.5 1573.65   173.1 1574.47
     176 1575.04   192.4 1578.34   211.6 1582.04   221.2 1583.85   230.8 1585.43
   240.4 1585.52   250.1 1583.72   259.7 1581.36   269.3 1579.79   278.9 1579.32
   288.5 1579.53   298.1 1581.58   307.8  1586.2   317.4 1592.04   346.2    1610
#Mann= 3 , 0 , 0
       0      .1       0     161    .045       0     176      .1       0
Bank Sta=161,176
XS Rating Curve= 0 ,0
Exp/Cntr=0.3,0.1

Type RM Length L Ch R = 1 ,11073.6 ,271,268.3,265.7
XS GIS Cut Line= 2
     1885957.331      352284.508     1885933.144      352593.991
#Sta/Elev= 29
       0    1580     9.7 1574.85    19.4 1569.98    29.1 1566.25    38.8 1564.69
    48.5 1565.06    58.2 1566.08    67.9 1566.94    77.6 1567.56    87.3 1567.97
      97  1568.2   106.7  1568.3   116.4 1568.26   126.1 1568.09   155.2 1567.21
   184.3 1566.18     194 1565.74   203.7 1564.89   223.1 1561.21   227.5 1560.84
   232.8  1560.4   242.5 1560.82   252.2 1562.06   261.9 1563.47   271.6 1565.02
   281.3 1567.39     291 1570.86   300.7 1574.72   310.4 1577.68
#Mann= 3 , 0 , 0
       0      .1       0   227.5    .045       0   242.5      .1       0
Bank Sta=227.5,242.5
XS Rating Curve= 0 ,0
Exp/Cntr=0.3,0.1

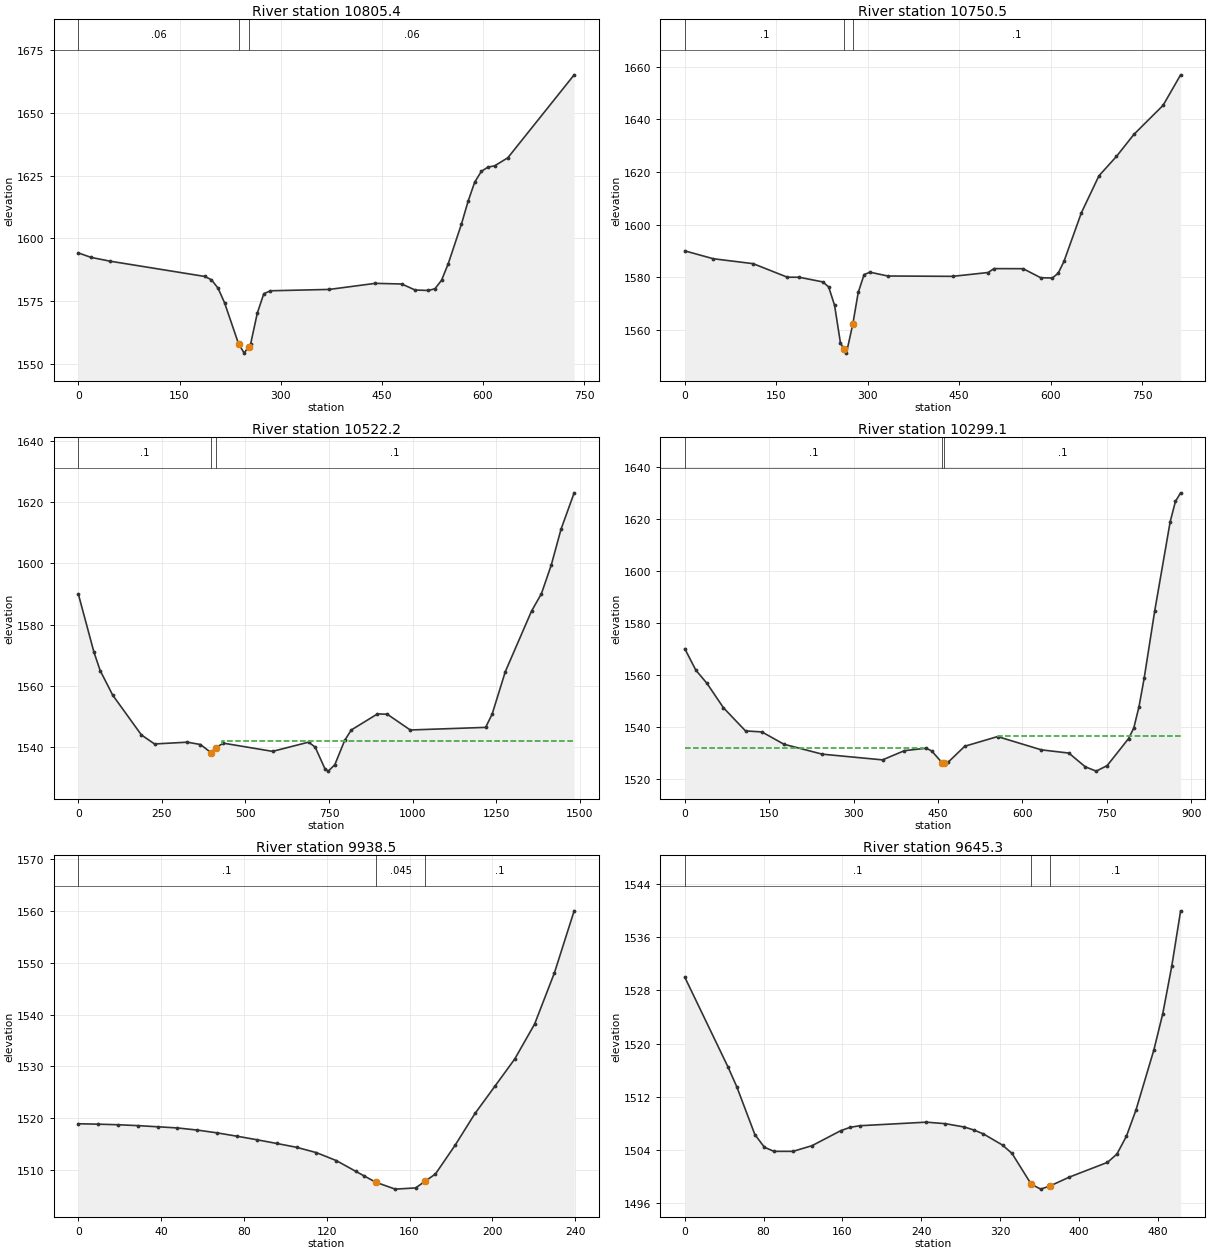
Type RM Length L Ch R = 1 ,10805.4 ,55.2,54.8,54.4
XS GIS Cut Line= 4
     1885706.719      352239.475     1885675.367      352404.752
     1885684.687      352666.759     1885936.659      352838.114
#Sta/Elev= 30
       0 1594.25    18.7 1592.49    46.7 1590.98   187.6 1584.89   197.4 1583.57
   207.1 1580.25   216.8 1574.44   237.5 1558.16   245.9 1554.42   252.5 1557.02
   255.6 1558.24   265.3 1570.29     275 1578.04   284.8  1579.2   372.1 1579.74
   440.2 1582.15   479.5  1581.9   499.2 1579.51   518.9 1579.32   528.7 1580.01
   538.5 1583.38   548.4 1589.95     568 1605.71   577.8 1614.72   587.7 1622.43
   597.5 1626.64   607.3 1628.36   617.2 1628.86   636.8 1632.07   735.1 1665.03
#Mann= 3 , 0 , 0
       0     .06       0   237.5    .045       0   252.5     .06       0
Bank Sta=237.5,252.5
XS Rating Curve= 0 ,0
Exp/Cntr=0.3,0.1

Type RM Length L Ch R = 1 ,10750.5 ,224.9,228.3,231.7
XS GIS Cut Line= 4
     1885652.107      352213.392     1885620.755      352378.669
     1885633.232      352707.891     1885895.426      352883.687
#Sta/Elev= 30
       0    1590    46.7 1587.01   112.2 1585.13   168.2 1579.98   187.6 1579.97
   226.4 1578.19     236 1576.29   245.7  1569.3   255.4  1554.9   260.7 1552.82
   265.1  1551.1   275.7 1562.24   284.5 1574.18   294.2    1581   303.9 1581.88
     333 1580.44   439.5 1580.31   497.7 1581.77   507.2 1583.25   555.1 1583.22
   583.8 1579.79   602.9 1579.68   612.5 1581.48     622 1585.98   650.7 1604.56
   679.4 1618.55   708.1 1625.92   736.8 1634.32   784.7 1645.39   813.4 1656.97
#Mann= 3 , 0 , 0
       0      .1       0   260.7    .045       0   275.7      .1       0
Bank Sta=260.7,275.7
XS Rating Curve= 0 ,0
Exp/Cntr=0.3,0.1

Type RM Length L Ch R = 1 ,10522.2 ,222.3,223.1,223
XS GIS Cut Line= 3
     1885506.711      352048.093     1885425.668      352173.741
     1885307.319      353502.176
#Sta/Elev= 30
       0 1589.99    46.7    1571    65.4 1564.96   102.8 1556.95   188.7 1543.94
     228 1540.99     326 1541.57   365.3 1540.81   396.8 1538.17   411.8 1539.82
   433.9 1541.25     581 1538.57   688.9 1541.58   708.5 1539.95   737.9 1532.84
   747.7 1532.11   767.3 1534.22   796.8 1542.16   816.4 1545.55   894.8 1550.81
   924.2 1550.71   992.9 1545.56  1218.4 1546.41    1238 1550.79  1277.3 1564.64
  1355.7 1584.42  1385.2 1590.09  1414.6 1599.43    1444  1611.2  1483.2 1623.07
#Mann= 3 , 0 , 0
       0      .1       0   396.8    .045       0   411.8      .1       0
#XS Ineff= 2 , 0
                          430.42         1541.82
Permanent Ineff=
       F       F
Bank Sta=396.8,411.8
XS Rating Curve= 0 ,0
Exp/Cntr=0.3,0.1

Type RM Length L Ch R = 1 ,10299.1 ,345.8,360.6,375.3
XS GIS Cut Line= 4
     1885289.357      351956.071     1885228.993       352033.49
     1885154.503      352701.155     1885093.519      352793.985
#Sta/Elev= 30
       0 1570.01    19.6 1561.78    39.3 1556.71    68.7 1547.29   107.9 1538.38
   137.1 1537.99   176.1 1533.26   244.2 1529.44   351.3 1527.24   390.3 1530.79
   429.2 1531.73   438.9 1530.63  457.36 1526.08  460.521525.969   468.2  1526.4
   497.4 1532.48   555.8 1536.21   633.7 1531.09   682.4 1529.86   711.6 1524.57
     731 1522.91   750.5 1525.04   788.5 1535.44   797.8 1539.52     807 1547.67
   816.3 1558.74   834.8 1584.35   862.5 1618.94   871.8 1626.71     881    1630
#Mann= 3 , 0 , 0
       0      .1       0  457.36    .045       0  460.52      .1       0
#XS Ineff= 2 , 0
          422.54 1531.74  556.34         1536.36
Permanent Ineff=
       F       F
Bank Sta=457.36,460.52
XS Rating Curve= 0 ,0
Exp/Cntr=0.3,0.1

Type RM Length L Ch R = 1 ,9938.5  ,295.3,293.2,290.7
XS GIS Cut Line= 2
     1884939.076       352228.54     1884776.243      352404.214
#Sta/Elev= 28
       0 1518.93     9.6 1518.85    19.2 1518.74    28.7 1518.57    38.3 1518.35
    47.9 1518.12    57.5 1517.71    67.1 1517.17    76.6 1516.53    86.2 1515.85
    95.8 1515.13   105.4 1514.39     115 1513.36   124.6 1511.83   134.1 1509.73
   138.1 1508.86   143.7 1507.64   153.1 1506.32   162.9 1506.55  167.61 1507.87
   172.5 1509.24     182 1514.79   191.6 1520.91   201.2 1526.16   210.8 1531.42
   220.4 1538.16     230 1548.08   239.5    1560
#Mann= 3 , 0 , 0
       0      .1       0   143.7    .045       0  167.61      .1       0
Bank Sta=143.7,167.61
XS Rating Curve= 0 ,0
Exp/Cntr=0.3,0.1

Type RM Length L Ch R = 1 ,9645.3  ,205.7,196.1,186.4
XS GIS Cut Line= 4
     1884824.228      351840.499     1884805.177       351898.92
     1884566.941      352215.895     1884549.868      352257.917
#Sta/Elev= 30
       0    1530    43.9 1516.46    52.7 1513.52    71.1  1506.3    80.8 1504.38
    90.5 1503.76   109.8 1503.76   129.2 1504.62   158.2 1506.87   167.8 1507.38
   177.5 1507.62   245.2 1508.16   264.6 1507.93   283.9 1507.42   293.6 1506.97
   303.2 1506.38   322.6  1504.7   332.2 1503.44   351.6 1498.82   361.3 1498.07
   370.9 1498.56   390.3 1499.88     429  1502.1   438.6 1503.34   448.3 1506.05
     458    1510   476.1 1519.02   485.2 1524.52   494.3 1531.66   503.3    1540
#Mann= 3 , 0 , 0
       0      .1       0   351.6    .045       0   370.9      .1       0
Bank Sta=351.6,370.9
XS Rating Curve= 0 ,0
Exp/Cntr=0.3,0.1

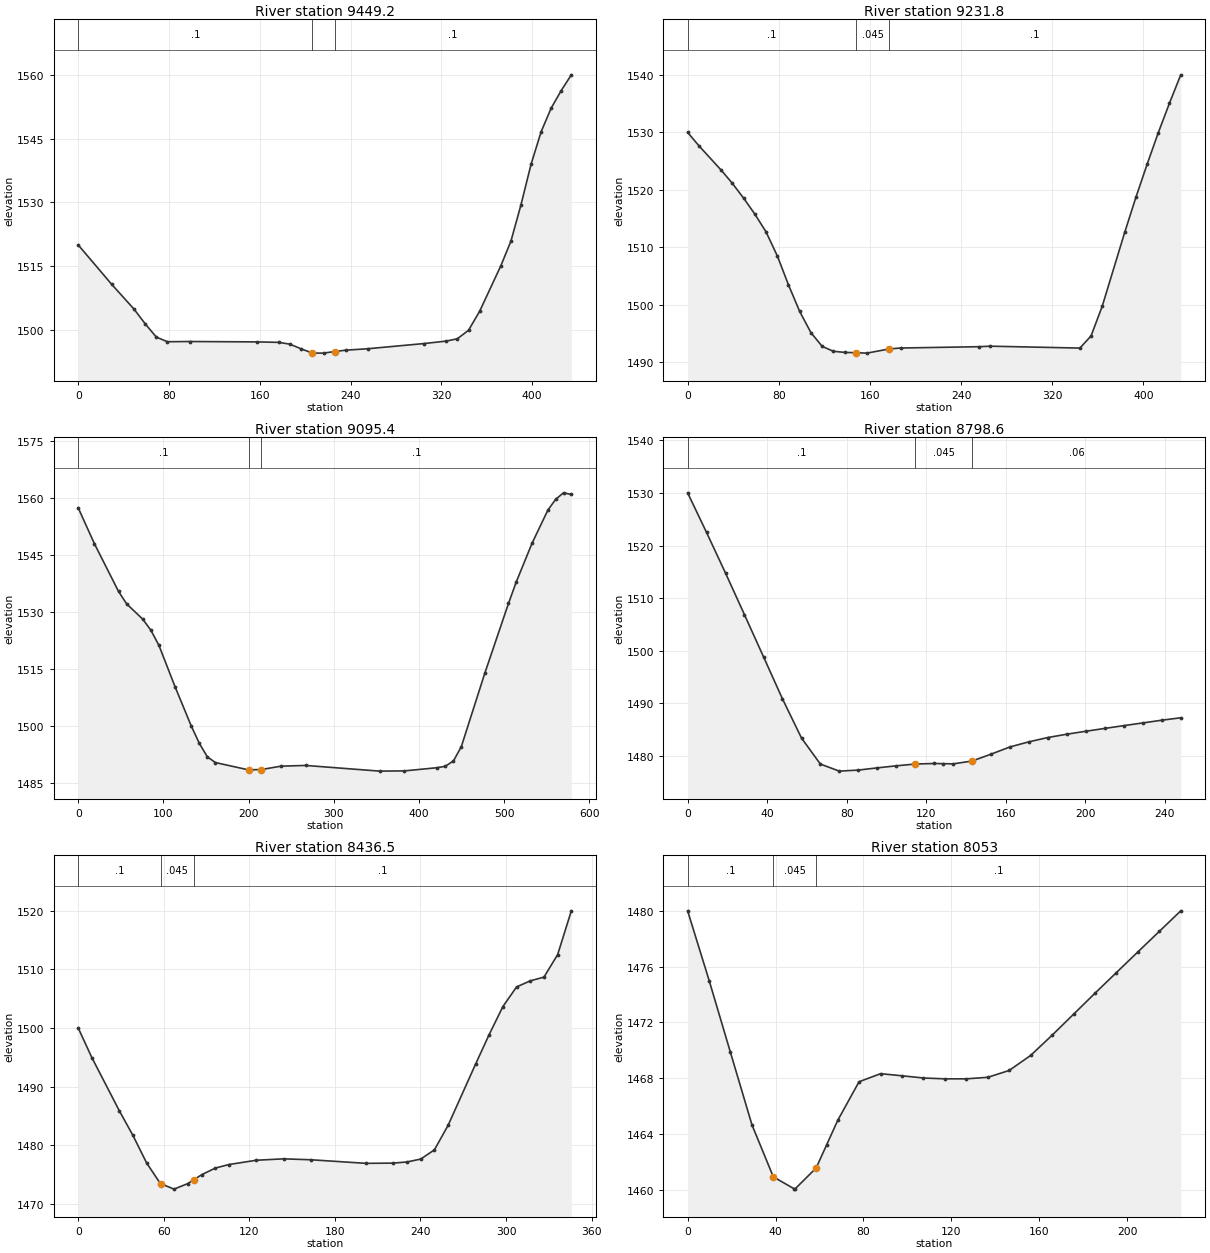
Type RM Length L Ch R = 1 ,9449.2  ,226.2,217.4,208.7
XS GIS Cut Line= 3
     1884498.998      351840.929      1884419.71      352195.805
     1884425.906      352266.484
#Sta/Elev= 29
       0    1520    29.5 1510.74    49.1 1504.94      59 1501.47    68.8 1498.34
    78.6 1497.24    98.3 1497.29   157.2  1497.2   176.9 1497.09   186.7 1496.66
   196.6 1495.55   206.4 1494.58   216.2 1494.56     226 1494.94   235.9 1495.25
   255.5  1495.6   304.7 1496.81   324.3 1497.39   334.1 1497.93     344 1499.94
   353.8 1504.41   372.5 1515.12   381.4 1520.92   390.2 1529.42   399.1 1538.97
     408 1546.63   416.8 1552.16   425.7 1556.31   434.6    1560
#Mann= 3 , 0 , 0
       0      .1       0   206.4    .045       0     226      .1       0
Bank Sta=206.4,226
XS Rating Curve= 0 ,0
Exp/Cntr=0.3,0.1

Type RM Length L Ch R = 1 ,9231.8  ,138.1,136.4,134.7
XS GIS Cut Line= 2
      1884220.27       351844.07     1884292.316      352270.688
#Sta/Elev= 29
       0    1530     9.8 1527.69    29.5 1523.41    39.3 1521.11    49.2 1518.52
      59 1515.76    68.8 1512.67    78.7 1508.49    88.5 1503.44    98.3 1498.82
   108.2 1495.12     118 1492.74   127.8 1491.87   137.7 1491.68   147.9 1491.62
   157.3 1491.55     177 1492.28   186.8 1492.44   255.7 1492.67   265.5 1492.76
   344.2 1492.43     354 1494.55   363.8 1499.72   383.5 1512.57   393.3 1518.66
   403.2 1524.45     413 1529.95   422.8 1535.09   432.7 1540.02
#Mann= 3 , 0 , 0
       0      .1       0   147.9    .045       0     177      .1       0
Bank Sta=147.9,177
XS Rating Curve= 0 ,0
Exp/Cntr=0.3,0.1

Type RM Length L Ch R = 1 ,9095.4  ,315.5,296.8,277.8
XS GIS Cut Line= 4
     1883990.044      351870.232     1884102.892      351985.249
     1884170.166      352256.517     1884274.333      352347.663
#Sta/Elev= 30
       0 1557.45      19 1548.01    47.4 1535.39    56.9 1532.12    75.8 1528.09
    85.3 1525.19    94.8 1521.18   113.7 1510.28   132.7 1499.95   142.2 1495.35
   151.6  1491.8   161.1 1490.28     200 1488.35     215 1488.44   238.2 1489.33
   267.1 1489.52   353.9 1488.02   382.8 1488.08   421.3 1488.92     431  1489.3
   440.6 1490.71   449.8 1494.46   477.5 1513.91   505.2 1532.23   514.4 1537.95
   532.9 1548.13   551.4 1556.83   560.6  1559.7   569.8 1561.41     579 1560.98
#Mann= 3 , 0 , 0
       0      .1       0     200    .045       0     215      .1       0
Bank Sta=200,215
XS Rating Curve= 0 ,0
Exp/Cntr=0.3,0.1

Type RM Length L Ch R = 1 ,8798.6  ,362.8,362.2,361.1
XS GIS Cut Line= 2
     1883808.687       352161.07     1884024.146      352284.096
#Sta/Elev= 29
       0 1530.03     9.5 1522.52    19.1 1514.75    28.6 1506.87    38.2 1498.85
    47.7 1490.89    57.3 1483.42    66.8 1478.48    76.3 1477.14    85.9 1477.34
    95.4 1477.76     105 1478.15   113.7 1478.46   114.5 1478.49     124 1478.59
   128.7 1478.56   133.6 1478.52   143.1 1479.06   152.7 1480.37   162.2 1481.74
   171.8 1482.72   181.3 1483.53   190.8 1484.16   200.4 1484.72   209.9 1485.26
   219.5 1485.79     229  1486.3   238.6 1486.82   248.1 1487.28
#Mann= 3 , 0 , 0
       0      .1       0   114.5    .045       0   143.1     .06       0
Bank Sta=114.5,143.1
XS Rating Curve= 0 ,0
Exp/Cntr=0.3,0.1

Type RM Length L Ch R = 1 ,8436.5  ,363.9,383.5,403
XS GIS Cut Line= 2
     1883690.547       352488.87     1883995.159      352652.657
#Sta/Elev= 30
       0    1500     9.6 1494.93    28.8 1485.88    38.4 1481.65      48 1476.95
    57.6 1473.45      58 1473.41    67.2 1472.49    76.9 1473.44   81.13  1474.1
    86.5 1474.94    96.1 1476.08   105.7 1476.69   124.9 1477.42   144.1 1477.66
   163.3  1477.5   201.8 1476.89     221 1476.93   230.6 1477.13   240.2 1477.62
   249.8  1479.2   259.4 1483.39   278.6  1493.8   288.2 1498.88   297.8 1503.65
   307.4    1507     317 1508.04   326.6 1508.68   336.2 1512.52   345.8 1519.99
#Mann= 3 , 0 , 0
       0      .1       0      58    .045       0   81.13      .1       0
Bank Sta=58,81.13
XS Rating Curve= 0 ,0
Exp/Cntr=0.3,0.1

Type RM Length L Ch R = 1 ,8053    ,236.7,250.5,264.1
XS GIS Cut Line= 2
     1883427.834      352658.771     1883477.046       352877.66
#Sta/Elev= 26
       0    1480     9.8    1475    19.5 1469.84    29.3 1464.64      39 1460.92
    48.3 1460.08    48.8 1460.04    58.5 1461.56    63.3 1463.23    68.3 1464.97
      78 1467.74    87.8 1468.32    97.5 1468.17   107.3 1468.01     117 1467.95
   126.8 1467.95   136.6 1468.06   146.3 1468.55   156.1 1469.63   165.8 1471.07
   175.6 1472.58   185.3 1474.08   195.1 1475.57   204.8 1477.04   214.6 1478.52
   224.4    1480
#Mann= 3 , 0 , 0
       0      .1       0      39    .045       0    58.5      .1       0
#XS Ineff= 2 , 0
                           95.77         1454.08
Permanent Ineff=
       F       F
Bank Sta=39,58.5
XS Rating Curve= 0 ,0
Exp/Cntr=0.3,0.1

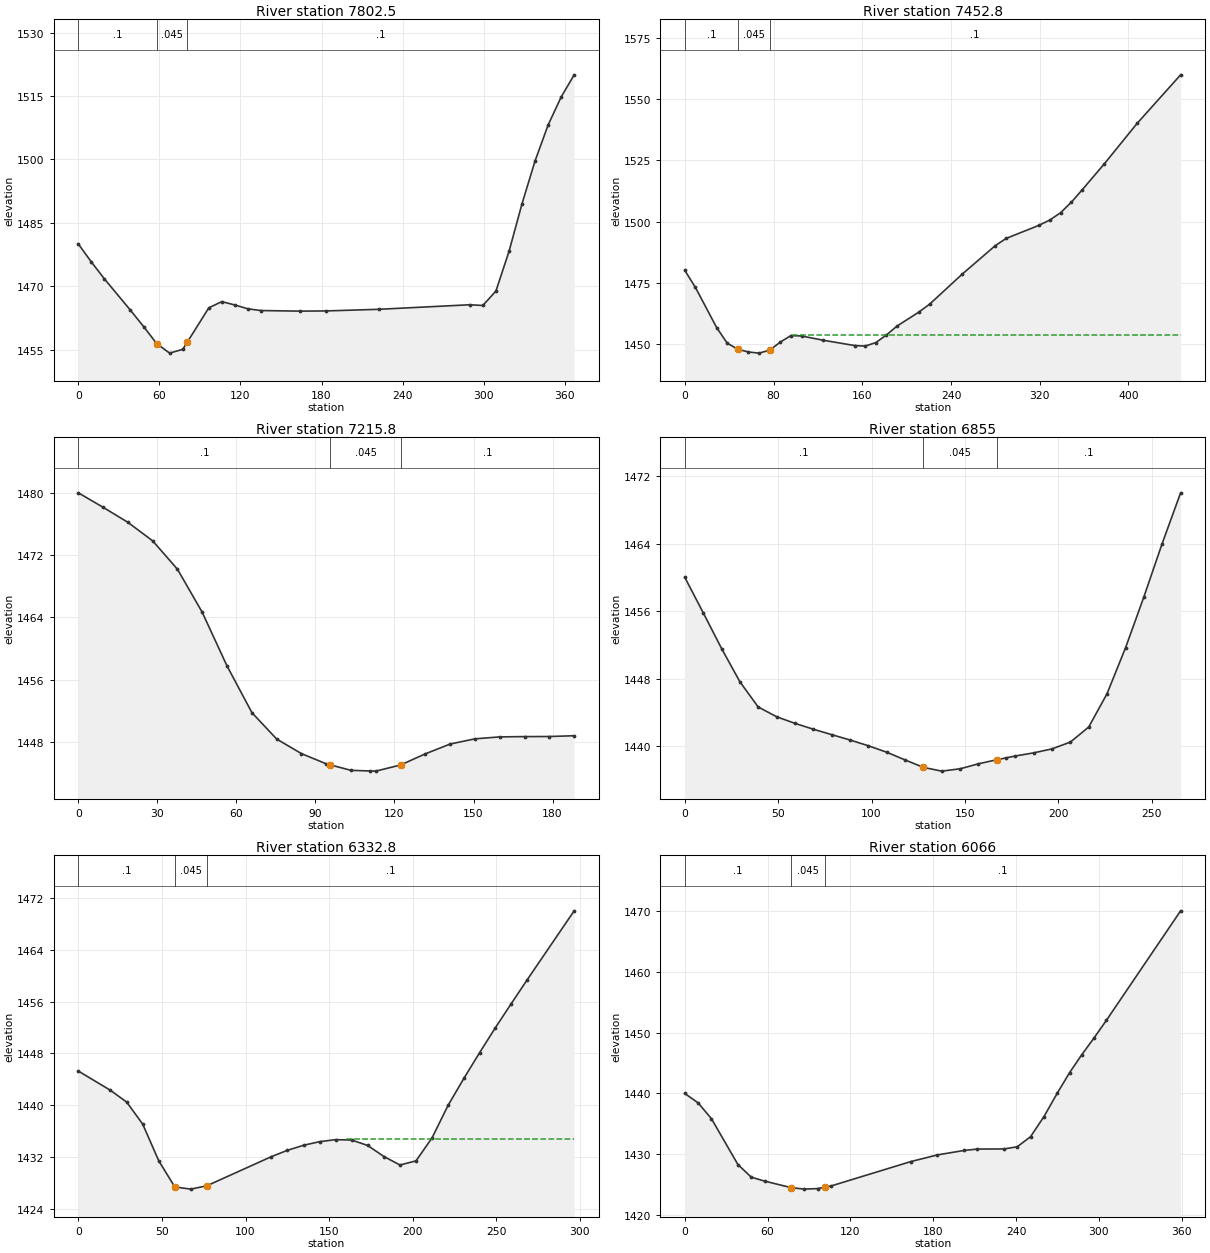
Type RM Length L Ch R = 1 ,7802.5  ,340.1,349.7,359.1
XS GIS Cut Line= 2
     1883221.144      352632.402     1883085.787      352973.585
#Sta/Elev= 26
       0    1480     9.7 1475.72    19.3 1471.75    38.6 1464.33    48.3 1460.48
      58 1456.44    67.6 1454.19    77.3 1455.09   80.561456.747    96.6 1464.91
   106.2 1466.37   115.9 1465.57   125.6 1464.66   135.2 1464.26   164.2 1464.12
   183.5 1464.17   222.2 1464.55   289.8 1465.63   299.4 1465.46   309.1 1468.87
   318.8 1478.26   328.4 1489.51   338.1 1499.68   347.7 1508.12   357.4 1514.77
     367    1520
#Mann= 3 , 0 , 0
       0      .1       0      58    .045       0   80.56      .1       0
Bank Sta=58,80.56
XS Rating Curve= 0 ,0
Exp/Cntr=0.3,0.1

Type RM Length L Ch R = 1 ,7452.8  ,229.6,237,244.5
XS GIS Cut Line= 3
     1882942.645      352491.782     1882800.521      352633.907
     1882658.586      352834.896
#Sta/Elev= 30
       0 1480.04     9.6 1473.03    28.7 1456.64    38.3 1450.22    47.9 1447.78
    57.4 1446.64      67 1446.18    76.6 1447.42    86.1  1450.7    95.7 1453.36
   105.3  1453.2   124.4 1451.48   153.1 1449.28   162.7 1449.07   172.3 1450.51
   181.8  1453.6   191.4 1457.28   210.8 1462.89   220.7  1466.2   250.2 1478.53
   279.7 1490.07   289.6 1493.07   319.1 1498.42   328.9 1500.58   338.8 1503.62
   348.6 1507.96   358.5  1513.1   378.2  1523.6   407.7 1540.11     447 1560.01
#Mann= 3 , 0 , 0
       0      .1       0    47.9    .045       0    76.6      .1       0
#XS Ineff= 2 , 0
                           97.18         1453.69
Permanent Ineff=
       F       F
Bank Sta=47.9,76.6
XS Rating Curve= 0 ,0
Exp/Cntr=0.3,0.1

Type RM Length L Ch R = 1 ,7215.8  ,368.8,360.9,352.4
XS GIS Cut Line= 2
     1882838.599      352311.707     1882669.979      352395.207
#Sta/Elev= 23
       0    1480     9.4 1478.14    18.8 1476.21    28.2 1473.83    37.6 1470.19
      47 1464.66    56.4 1457.77    65.9 1451.73    75.3 1448.34    84.7 1446.47
    94.1 1445.16    95.7 1445.02   103.5 1444.32   110.7 1444.24   112.9 1444.22
   122.3 1445.01   131.7 1446.44   141.1  1447.7   150.5 1448.37   159.9 1448.62
   169.4 1448.66   178.8 1448.67   188.2 1448.77
#Mann= 3 , 0 , 0
       0      .1       0    95.7    .045       0   122.3      .1       0
#XS Ineff= 2 , 0
                          158.87         1435.01
Permanent Ineff=
       F       F
Bank Sta=95.7,122.3
XS Rating Curve= 0 ,0
Exp/Cntr=0.3,0.1

Type RM Length L Ch R = 1 ,6855    ,532.7,522.2,511.6
XS GIS Cut Line= 2
     1882618.472      352058.091     1882433.752      352248.735
#Sta/Elev= 29
       0    1460     9.8 1455.84    19.7 1451.58    29.5 1447.65    39.3 1444.67
    49.2 1443.51      59 1442.73    68.8 1442.04    78.6  1441.4    88.5 1440.76
    98.3 1440.08   108.2 1439.31     118  1438.4   127.8 1437.52   137.6 1437.08
   147.5 1437.36   157.1 1437.94   167.1 1438.43   172.1 1438.65     177 1438.87
   186.8 1439.24   196.6 1439.71   206.5 1440.52   216.3  1442.3   226.1 1446.24
     236 1451.67   245.8 1457.67   255.6 1463.99   265.5    1470
#Mann= 3 , 0 , 0
       0      .1       0   127.8    .045       0   167.1      .1       0
Bank Sta=127.8,167.1
XS Rating Curve= 0 ,0
Exp/Cntr=0.3,0.1

Type RM Length L Ch R = 1 ,6332.8  ,264.7,266.8,268.8
XS GIS Cut Line= 3
     1882107.479      351834.443     1882040.666      352045.352
     1882035.911      352120.557
#Sta/Elev= 26
       0 1445.28    19.2 1442.31    28.9  1440.5    38.5  1437.1    48.1 1431.44
    57.7 1427.41    67.3 1427.07      77  1427.6   115.4 1432.07     125 1433.05
   134.7 1433.83   144.3 1434.39   153.9  1434.7   163.5 1434.64   173.1  1433.8
   182.8  1432.1   192.4 1430.79     202 1431.43   211.6 1434.98   221.2    1440
   230.7 1444.18   240.1 1448.14   249.5 1451.97   258.9 1455.65   268.3 1459.28
   296.6 1469.99
#Mann= 3 , 0 , 0
       0      .1       0    57.7    .045       0      77      .1       0
#XS Ineff= 2 , 0
                          160.56         1434.74
Permanent Ineff=
       F       F
Bank Sta=57.7,77
XS Rating Curve= 0 ,0
Exp/Cntr=0.3,0.1

Type RM Length L Ch R = 1 ,6066    ,349.5,352.2,355
XS GIS Cut Line= 3
     1881862.893      351761.681     1881760.023      352011.039
     1881741.403      352098.555
#Sta/Elev= 25
       0    1440     9.6 1438.47    19.3 1435.86    38.5 1428.32    48.2 1426.25
    57.8 1425.61    77.1 1424.53    86.7 1424.29    96.3 1424.38   101.9 1424.63
     106 1424.81   163.8 1428.82     183 1429.91   202.3 1430.64   211.9 1430.87
   231.2 1430.89   240.8 1431.24   250.5 1432.91   260.1 1436.17   269.7    1440
   278.7  1443.4   287.6 1446.37   296.6 1449.16   305.5 1452.04   359.2    1470
#Mann= 3 , 0 , 0
       0      .1       0    77.1    .045       0   101.9      .1       0
Bank Sta=77.1,101.9
XS Rating Curve= 0 ,0
Exp/Cntr=0.3,0.1

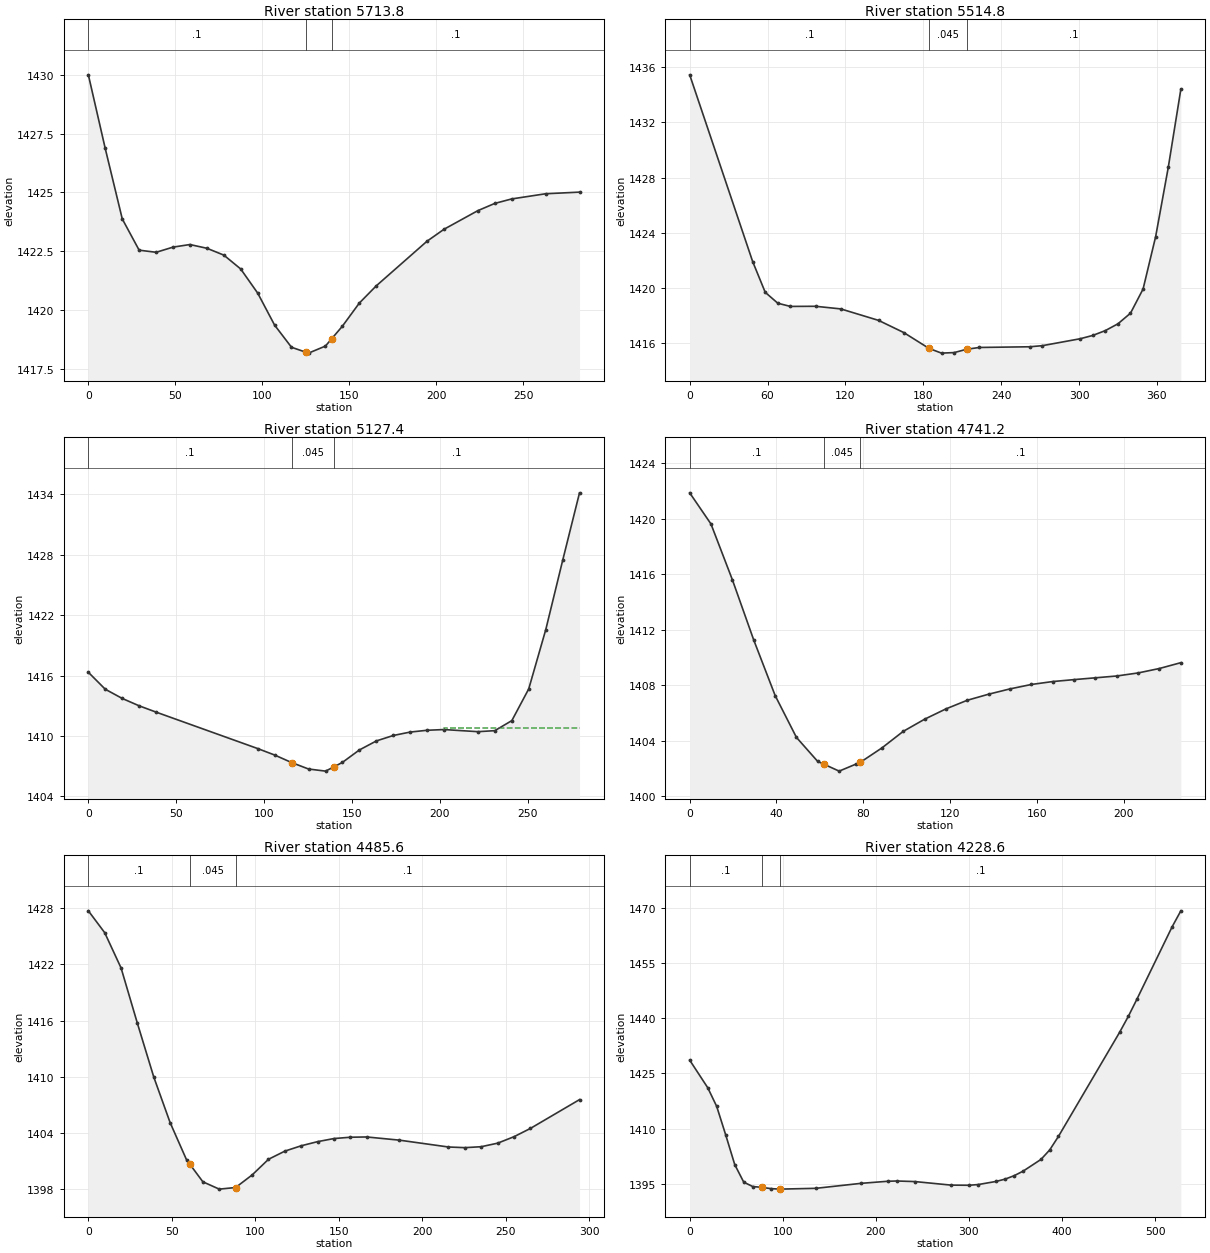
Type RM Length L Ch R = 1 ,5713.8  ,191.8,199,206.2
XS GIS Cut Line= 2
     1881557.778      351625.426     1881418.243      351870.901
#Sta/Elev= 27
       0    1430     9.7 1426.87    19.5 1423.87    29.2 1422.54      39 1422.45
    48.7 1422.67    58.4 1422.78    68.2 1422.62    77.9 1422.33    87.6 1421.74
    97.4 1420.71   107.1 1419.35   116.8 1418.41     125  1418.2   126.6 1418.16
   136.3 1418.46     140 1418.78     146  1419.3   155.8 1420.29   165.5 1421.02
   194.7 1422.92   204.5 1423.43   223.9 1424.22   233.7 1424.53   243.4 1424.72
   262.9 1424.94   282.4 1425.01
#Mann= 3 , 0 , 0
       0      .1       0     125    .045       0     140      .1       0
#XS Ineff= 2 , 0
                          201.13         1410.74
Permanent Ineff=
       F       F
Bank Sta=125,140
XS Rating Curve= 0 ,0
Exp/Cntr=0.3,0.1

Type RM Length L Ch R = 1 ,5514.8  ,384.4,387.4,390.2
XS GIS Cut Line= 2
     1881470.326      351514.998     1881192.548      351771.943
#Sta/Elev= 25
       0 1435.44    48.5 1421.93    58.2  1419.7    67.9 1418.91    77.6 1418.68
      97 1418.69   116.4  1418.5   145.5 1417.67   164.9 1416.79   184.4 1415.64
     194  1415.3   203.8 1415.34   213.4 1415.58   223.2 1415.71     262 1415.76
   271.7 1415.84   300.8 1416.34   310.5 1416.58   320.2 1416.93   329.9 1417.42
   339.6 1418.19   349.3 1419.94     359 1423.74   368.7 1428.74   378.4  1434.4
#Mann= 3 , 0 , 0
       0      .1       0   184.4    .045       0   213.4      .1       0
Bank Sta=184.4,213.4
XS Rating Curve= 0 ,0
Exp/Cntr=0.3,0.1

Type RM Length L Ch R = 1 ,5127.4  ,391.4,386.2,380.3
XS GIS Cut Line= 2
     1881166.507      351296.248     1880940.812      351461.179
#Sta/Elev= 25
       0 1416.32     9.6 1414.64    19.3 1413.72    28.9 1412.99    38.6 1412.36
    96.4 1408.74     106  1408.1   115.7 1407.35   125.3 1406.71     135  1406.5
     140 1406.95   144.6 1407.37   154.2  1408.6   163.9  1409.5   173.5 1410.04
   183.1 1410.38   192.8 1410.56   202.4 1410.63   221.7 1410.42   231.3 1410.52
     241 1411.52   250.6 1414.67   260.3 1420.56   269.9 1427.43   279.5 1434.15
#Mann= 3 , 0 , 0
       0      .1       0   115.7    .045       0     140      .1       0
#XS Ineff= 2 , 0
                          202.39         1410.79
Permanent Ineff=
       F       F
Bank Sta=115.7,140
XS Rating Curve= 0 ,0
Exp/Cntr=0.3,0.1

Type RM Length L Ch R = 1 ,4741.2  ,259.7,255.7,252.3
XS GIS Cut Line= 2
      1880874.84      351023.679     1880725.534      351193.818
#Sta/Elev= 26
       0 1421.86     9.8 1419.62    19.7 1415.59    29.5 1411.27    39.4 1407.26
    49.2 1404.25      59 1402.52    61.7 1402.33    68.9 1401.82    76.7 1402.33
    78.7 1402.46    88.6 1403.49    98.4 1404.68   108.3 1405.56   118.1  1406.3
   127.9 1406.92   137.8 1407.36   147.6 1407.74   157.5 1408.06   167.3 1408.27
   177.2 1408.41     187 1408.54   196.8 1408.67   206.7 1408.89   216.5 1409.21
   226.4 1409.63
#Mann= 3 , 0 , 0
       0      .1       0    61.7    .045       0    78.7      .1       0
Bank Sta=61.7,78.7
XS Rating Curve= 0 ,0
Exp/Cntr=0.3,0.1

Type RM Length L Ch R = 1 ,4485.6  ,258.8,257,255.2
XS GIS Cut Line= 2
      1880687.34      350839.651     1880538.034      351093.123
#Sta/Elev= 27
       0 1427.69     9.8 1425.36    19.6  1421.6    29.4 1415.69    39.2 1409.97
      49 1405.11    58.8 1401.16   60.851400.668    68.6 1398.81    78.4 1398.03
    88.2  1398.2    98.1 1399.54   107.9 1401.21   117.7 1402.08   127.5 1402.65
   137.3 1403.09   147.1 1403.42   156.9 1403.56   166.7 1403.59   186.3 1403.25
   215.7 1402.52   225.5 1402.45   235.3 1402.55   245.2 1402.93     255 1403.62
   264.8  1404.5   294.2 1407.57
#Mann= 3 , 0 , 0
       0      .1       0   60.85    .045       0    88.2      .1       0
Bank Sta=60.85,88.2
XS Rating Curve= 0 ,0
Exp/Cntr=0.3,0.1

Type RM Length L Ch R = 1 ,4228.6  ,539.8,537.2,534.6
XS GIS Cut Line= 3
     1880459.909      350709.443      1880299.42      351040.568
     1880279.354      351199.026
#Sta/Elev= 30
       0 1428.58    19.4 1421.08      29 1416.02    38.7 1408.26    48.4  1400.2
    58.1 1395.41    67.8 1394.23    77.5 1394.02    87.2 1393.67    96.8 1393.53
   135.6 1393.75     184  1395.1     213 1395.67   222.7 1395.74   242.1 1395.58
   280.8 1394.62   300.2 1394.58   309.9 1394.77   329.2 1395.62   338.9 1396.25
   348.6 1397.18   358.3 1398.43   377.4  1401.6   386.8 1404.18   396.2 1407.86
   461.9 1436.14   471.3 1440.49   480.7 1445.25   518.3  1464.8   527.7 1469.15
#Mann= 3 , 0 , 0
       0      .1       0    77.5    .045       0    96.8      .1       0
Bank Sta=77.5,96.8
XS Rating Curve= 0 ,0
Exp/Cntr=0.3,0.1