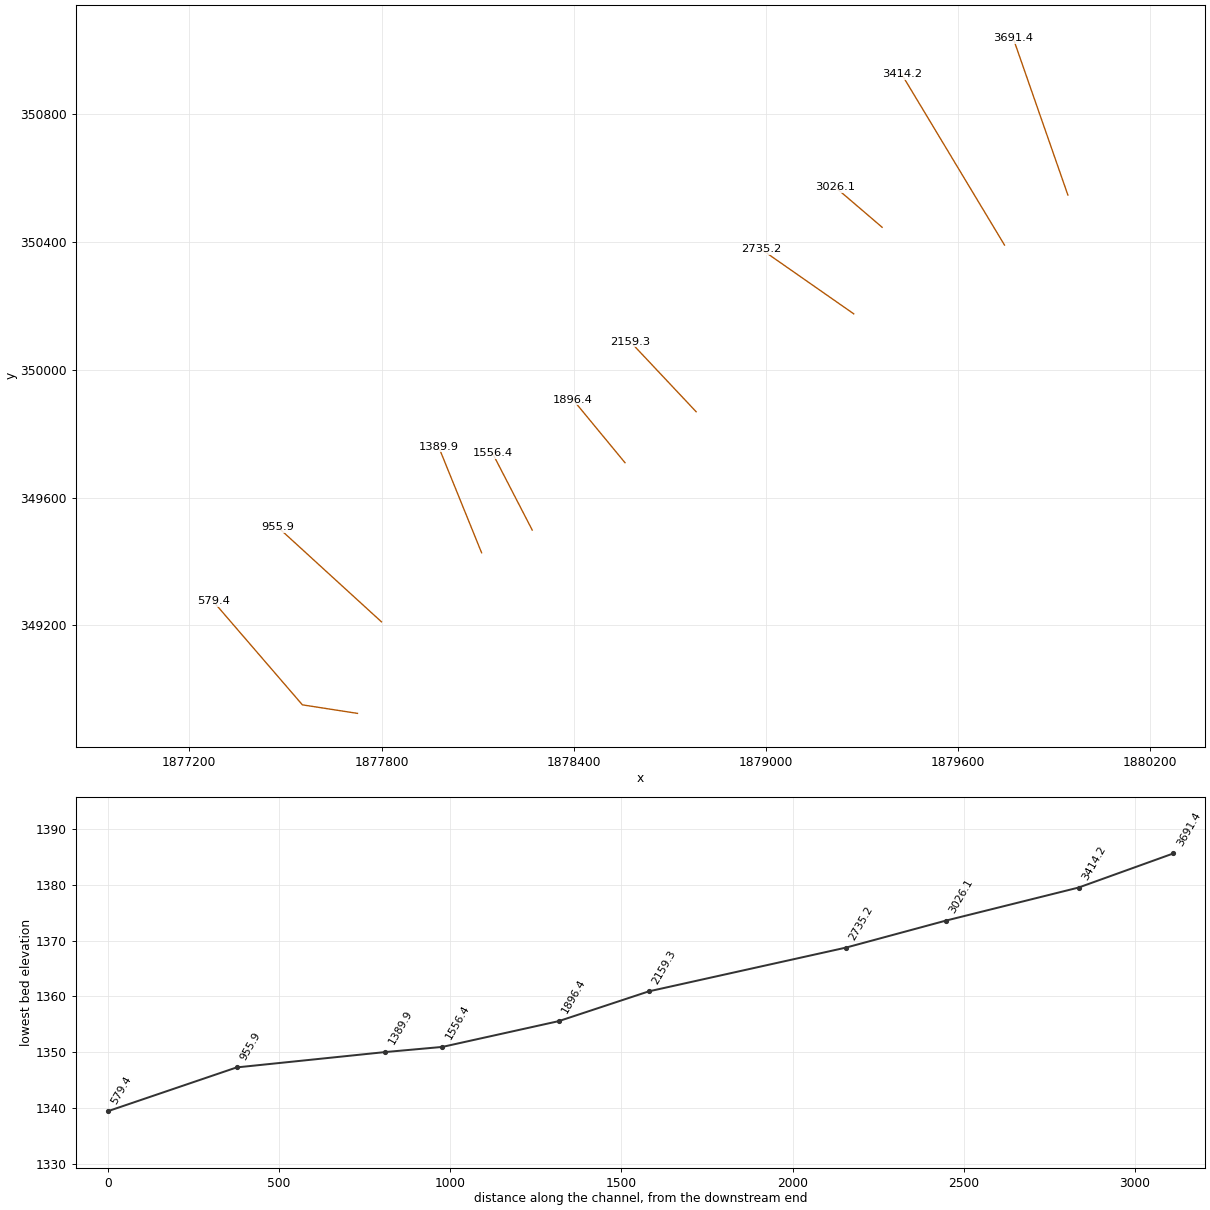
HEC-RAS study SQUIRESCRK.prj: SQUIRESCRK

--- SQUIRESCRK.g01 (geometry) --- (continued)

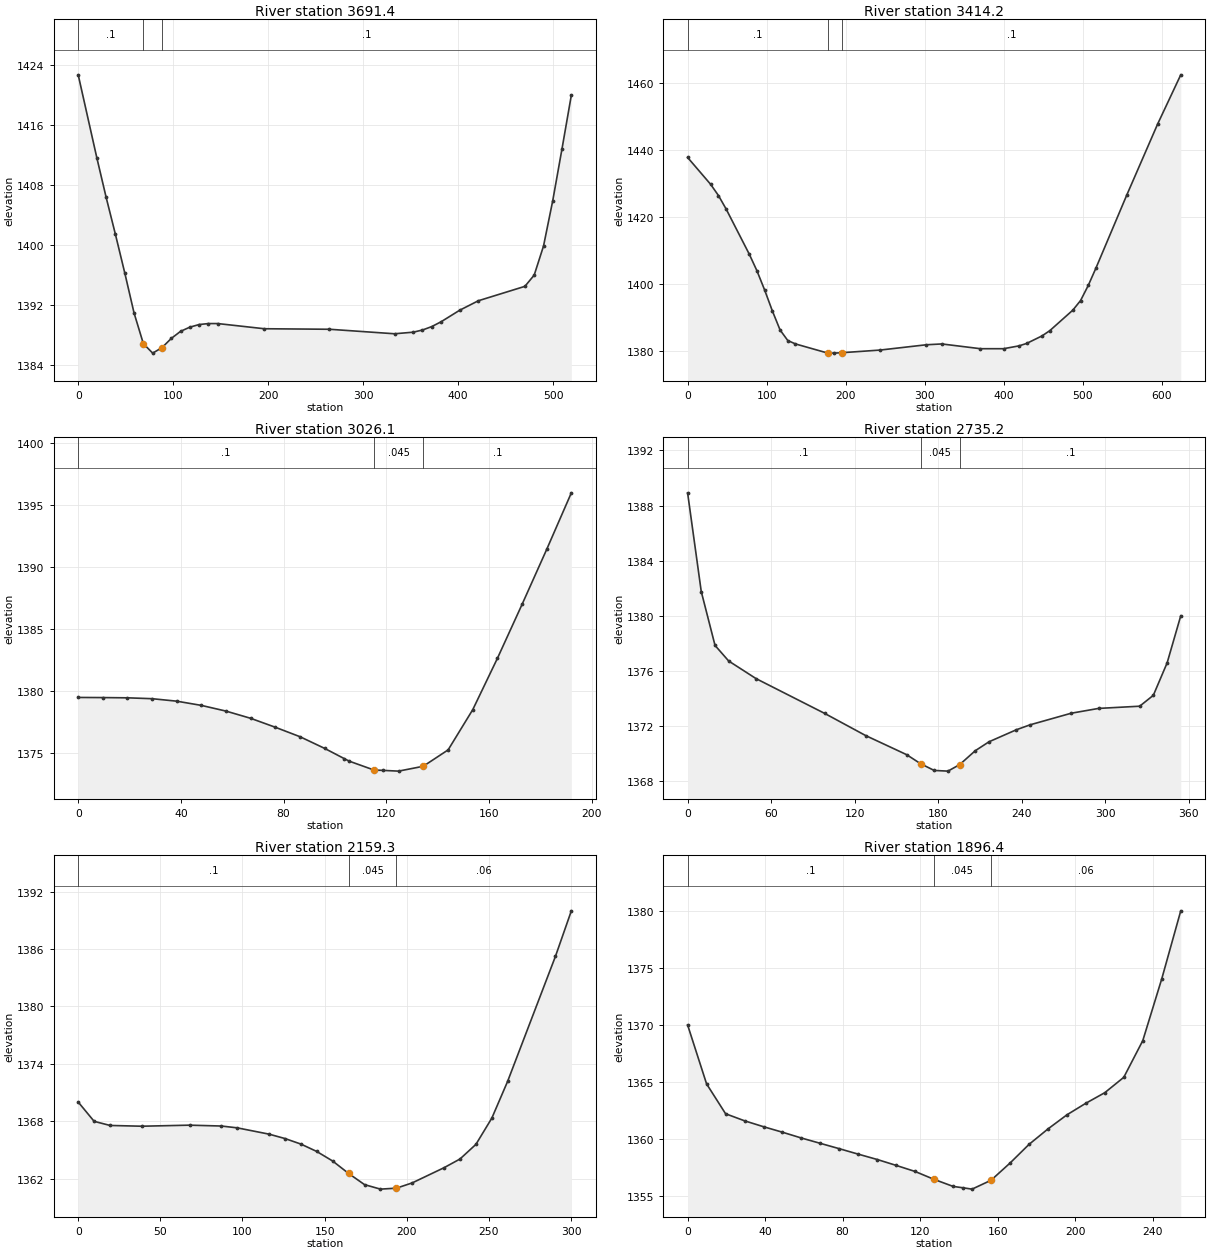
Type RM Length L Ch R = 1 ,3691.4  ,272.3,277.2,282
XS GIS Cut Line= 2
     1879942.548      350546.248     1879771.951      351036.548
#Sta/Elev= 30
       0 1422.69    19.6 1411.64    29.4 1406.37    39.2 1401.42      49  1396.3
    58.8 1390.95    68.6 1386.86    78.4  1385.6    88.2 1386.33      98 1387.56
   107.7  1388.5   117.5 1389.06   127.3 1389.41   137.1 1389.54   146.9 1389.54
   195.9 1388.85   264.5 1388.78     333 1388.18   352.6 1388.39   362.4 1388.68
   372.2 1389.14     382 1389.78   401.6 1391.32   421.2 1392.58   470.2  1394.5
     480    1396   489.8 1399.87   499.5 1405.91   509.3 1412.86   519.1 1419.98
#Mann= 3 , 0 , 0
       0      .1       0    68.6    .045       0    88.2      .1       0
Bank Sta=68.6,88.2
XS Rating Curve= 0 ,0
Exp/Cntr=0.3,0.1

Type RM Length L Ch R = 1 ,3414.2  ,380.4,388.1,395.9
XS GIS Cut Line= 2
     1879744.632      350389.998     1879423.451      350924.721
#Sta/Elev= 30
       0  1437.9    29.2 1429.86      39 1426.54    48.7 1422.52      78 1409.03
    87.7 1404.07    97.5 1398.29   107.2 1392.09     117 1386.38   126.7 1383.25
   136.4 1382.23   177.11379.503   185.2 1379.48   195.51379.609   243.7  1380.4
   302.1 1381.98   321.6 1382.22   370.4  1380.8   399.6  1380.8   419.1 1381.64
   428.8 1382.37   448.3 1384.62   458.1 1386.18   487.3 1392.32   497.1 1395.19
   506.8 1399.69   516.6 1404.92   555.5 1426.67   594.5 1447.85   623.8 1462.57
#Mann= 3 , 0 , 0
       0      .1       0   177.1    .045       0   195.5      .1       0
Bank Sta=177.1,195.5
XS Rating Curve= 0 ,0
Exp/Cntr=0.3,0.1

Type RM Length L Ch R = 1 ,3026.1  ,288.9,290.9,292.8
XS GIS Cut Line= 2
     1879362.687      350445.554     1879216.854      350570.554
#Sta/Elev= 23
       0 1379.48     9.6 1379.47    19.2 1379.45    28.8 1379.38    38.4 1379.18
      48 1378.84    57.6 1378.38    67.2  1377.8    76.8 1377.08    86.4 1376.32
      96 1375.38   103.7 1374.55   105.6 1374.35   115.2 1373.64   118.7 1373.61
   124.8 1373.55   134.4 1373.94   144.1 1375.26   153.7  1378.5   163.3 1382.63
   172.9 1386.97   182.5  1391.4   192.1 1395.95
#Mann= 3 , 0 , 0
       0      .1       0   115.2    .045       0   134.4      .1       0
Bank Sta=115.2,134.4
XS Rating Curve= 0 ,0
Exp/Cntr=0.3,0.1

Type RM Length L Ch R = 1 ,2735.2  ,580.1,575.9,571.8
XS GIS Cut Line= 2
     1879274.146      350174.721     1878983.902      350377.764
#Sta/Elev= 22
       0 1388.92     9.8 1381.76    19.7 1377.85    29.5 1376.72    49.2 1375.44
    98.4 1372.92   127.9 1371.31   157.4 1369.92   167.3 1369.27   177.1 1368.78
     187 1368.73   195.5 1369.21   206.6 1370.21   216.5 1370.86   236.1 1371.73
     246 1372.09   275.5 1372.93   295.2 1373.28   324.7 1373.44   334.5 1374.23
   344.4 1376.58   354.2    1380
#Mann= 3 , 0 , 0
       0      .1       0   167.3    .045       0   195.5      .1       0
Bank Sta=167.3,195.5
XS Rating Curve= 0 ,0
Exp/Cntr=0.3,0.1

Type RM Length L Ch R = 1 ,2159.3  ,264.4,262.9,261.5
XS GIS Cut Line= 2
     1878782.221       349868.47     1878576.777      350087.325
#Sta/Elev= 24
       0    1370     9.7 1367.98    19.4 1367.55    38.7 1367.47    67.8 1367.58
    87.2 1367.49    96.8  1367.3   116.2 1366.64   125.9 1366.18   135.6  1365.6
   145.2 1364.83   154.9 1363.83   164.6 1362.53   174.3 1361.36     184 1360.89
   193.7 1360.99   203.3 1361.54   222.7 1363.13   232.4 1364.04   242.1 1365.57
   251.8 1368.32   261.4 1372.16   290.5 1385.23   300.2    1390
#Mann= 3 , 0 , 0
       0      .1       0   164.6    .045       0   193.7     .06       0
Bank Sta=164.6,193.7
XS Rating Curve= 0 ,0
Exp/Cntr=0.3,0.1

Type RM Length L Ch R = 1 ,1896.4  ,345,340,335
XS GIS Cut Line= 2
     1878560.098      349709.061     1878398.368      349905.529
#Sta/Elev= 28
       0 1369.98     9.8  1364.8    19.6 1362.18    29.4 1361.56    39.2 1361.04
    48.9 1360.56    58.7 1360.05    68.5 1359.58    78.3 1359.11    88.1 1358.63
    97.9 1358.16   107.7 1357.64   117.4 1357.11     127 1356.43     137  1355.8
     142 1355.68   146.8 1355.56   156.6 1356.34   166.4 1357.85   176.2 1359.49
     186 1360.85   195.8 1362.09   205.5  1363.1   215.3 1364.03   225.1 1365.38
   234.9  1368.6   244.7 1374.03   254.5    1380
#Mann= 3 , 0 , 0
       0      .1       0     127    .045       0   156.6     .06       0
Bank Sta=127,156.6
XS Rating Curve= 0 ,0
Exp/Cntr=0.3,0.1

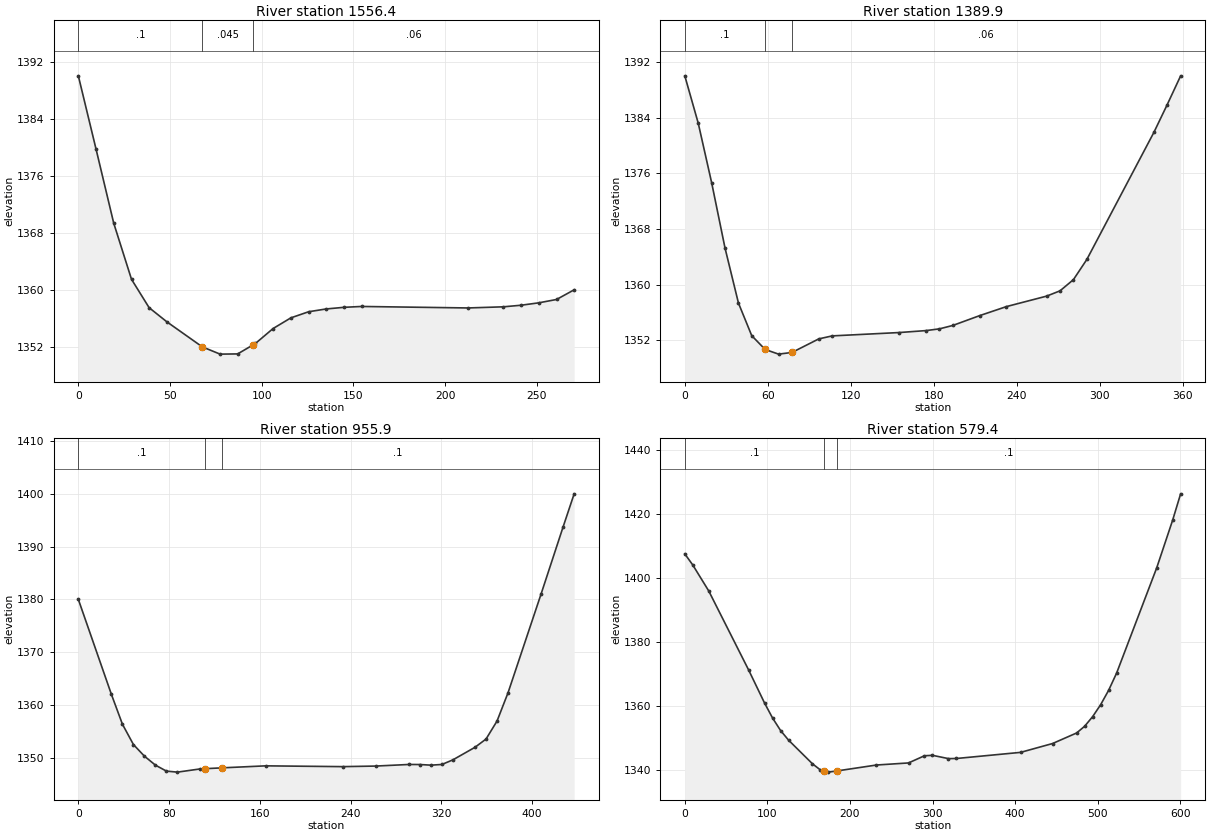
Type RM Length L Ch R = 1 ,1556.4  ,168.4,166.5,164.6
XS GIS Cut Line= 2
     1878270.417      349498.555     1878146.424      349738.883
#Sta/Elev= 23
       0    1390     9.7 1379.67    19.3 1369.32      29 1361.44    38.6 1357.46
    48.3 1355.47    67.6 1351.96    77.3 1350.94    86.9 1350.97    95.5 1352.27
    96.6 1352.44   106.2 1354.53   115.9 1356.03   125.6 1356.89   135.2 1357.28
   144.9 1357.51   154.5 1357.63   212.5 1357.42   231.8 1357.58   241.4  1357.8
   251.1 1358.14   260.8 1358.61   270.4 1359.97
#Mann= 3 , 0 , 0
       0      .1       0    67.6    .045       0    95.5     .06       0
Bank Sta=67.6,95.5
XS Rating Curve= 0 ,0
Exp/Cntr=0.3,0.1

Type RM Length L Ch R = 1 ,1389.9  ,423.8,434,444.3
XS GIS Cut Line= 2
      1878112.44      349427.385     1877977.928      349759.742
#Sta/Elev= 24
       0 1389.99     9.7  1383.2    19.4 1374.65    29.1 1365.24    38.8 1357.35
    48.4 1352.67    58.1 1350.69    67.8 1350.02    77.5 1350.26    96.9 1352.21
   106.6 1352.64     155 1353.12   174.4  1353.4   184.1 1353.65   193.8 1354.14
   213.2 1355.55   232.6 1356.85   261.6 1358.35   271.3 1359.11     281 1360.72
   290.7 1363.62   339.2 1381.88   348.8 1385.85   358.5 1389.98
#Mann= 3 , 0 , 0
       0      .1       0    58.1    .045       0    77.5     .06       0
Bank Sta=58.1,77.5
XS Rating Curve= 0 ,0
Exp/Cntr=0.3,0.1

Type RM Length L Ch R = 1 ,955.9   ,364.8,376.5,372.7
XS GIS Cut Line= 2
     1877799.853      349211.351     1877477.368      349506.623
#Sta/Elev= 26
       0    1380    29.2 1361.98    38.9 1356.34    48.6 1352.49    58.3 1350.29
      68 1348.59    77.7 1347.46    87.4 1347.27   106.9 1347.86   111.7 1347.92
   126.7 1348.08   165.2 1348.46   233.2 1348.31   262.4 1348.42   291.5 1348.72
   301.2 1348.71   310.9 1348.59   320.6 1348.72   330.4 1349.61   349.8 1351.98
   359.5 1353.54   369.2 1356.95   378.9 1362.31   408.1 1381.06   427.5 1393.76
   437.2    1400
#Mann= 3 , 0 , 0
       0      .1       0   111.7    .045       0   126.7      .1       0
Bank Sta=111.7,126.7
XS Rating Curve= 0 ,0
Exp/Cntr=0.3,0.1

Type RM Length L Ch R = 1 ,579.4   ,565.6,579.4,608.3
XS GIS Cut Line= 3
        1877725.         348925.     1877553.125      348951.656
        1877275.         349275.
#Sta/Elev= 30
       0 1407.59     9.7  1404.1      29    1396    77.3 1371.32    96.6 1360.99
   106.3 1356.31     116 1352.41   125.6 1349.42   154.6 1342.02   164.3 1340.08
   168.9 1339.76   173.9 1339.42   183.9 1339.78   232.1 1341.64   270.9 1342.29
   290.2 1344.53   299.9 1344.67   319.3 1343.64     329 1343.68   406.6 1345.59
   445.3 1348.35   474.4 1351.64   484.1 1353.73   493.8 1356.73   503.5 1360.46
   513.2 1364.96   522.9 1370.36   571.4 1403.19   590.7 1418.08   600.4 1426.34
#Mann= 3 , 0 , 0
       0      .1       0   168.9    .045       0   183.9      .1       0
Bank Sta=168.9,183.9
XS Rating Curve= 0 ,0
Exp/Cntr=0.3,0.1

Chan Stop Cuts=-1
Use User Specified Reach Order=0
Composite Channel Slope=5